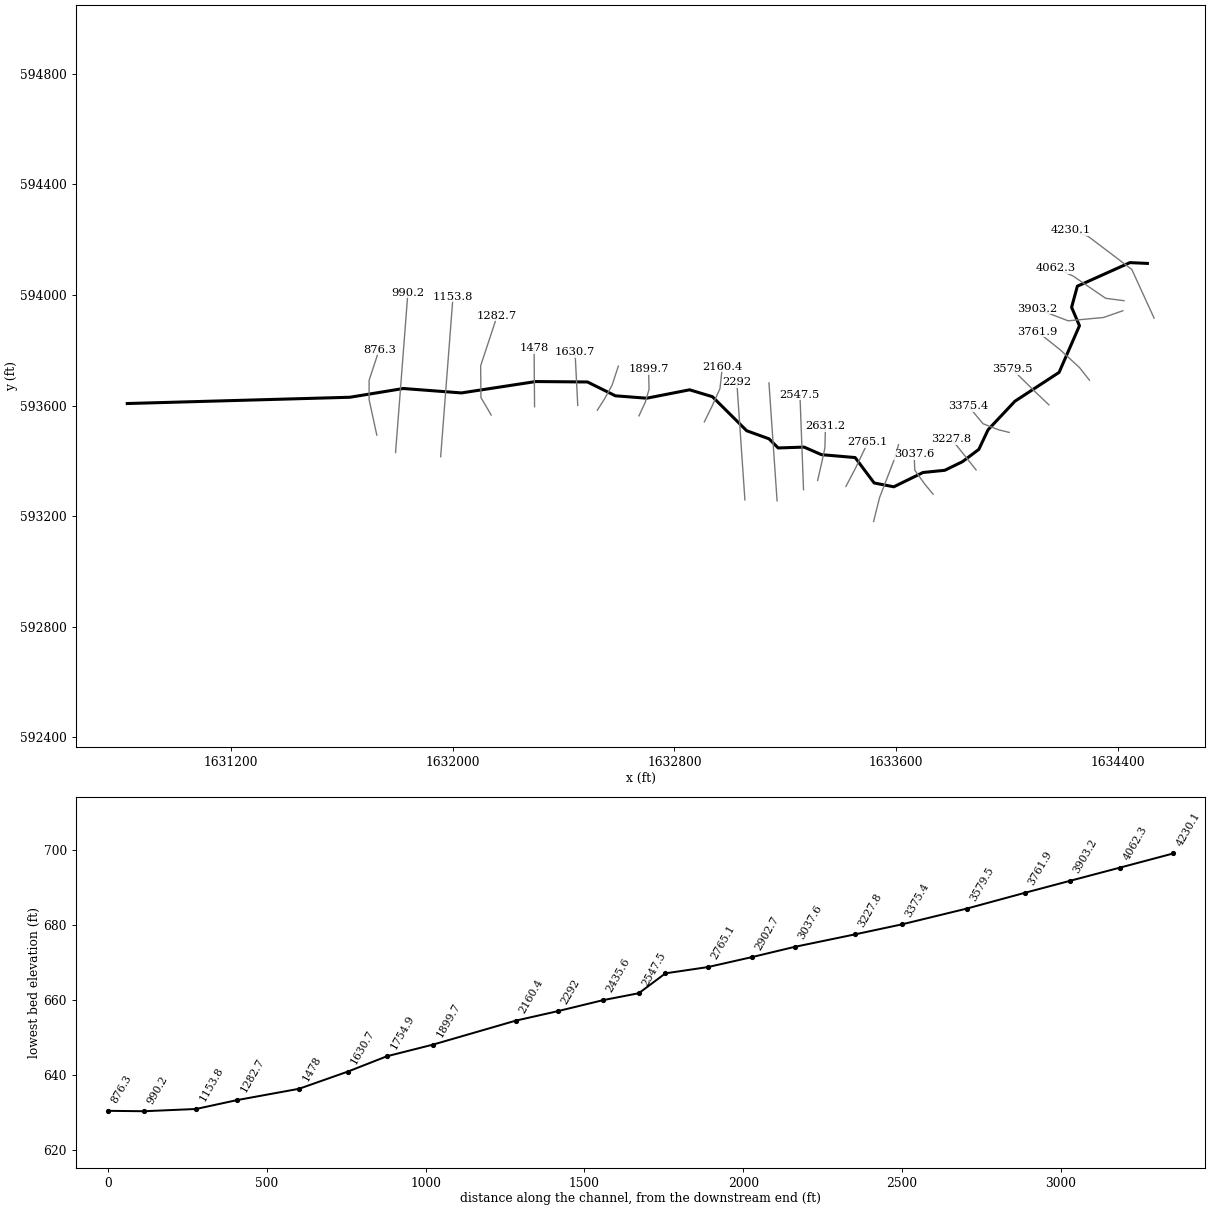
--- GLENNSRUN.prj (project) ---

Proj Title=GLENNSRUN
Current Plan=p01
Default Exp/Contr=0,0
English Units
Geom File=g01
Flow File=f01
Plan File=p01
BEGIN DESCRIPTION:
END DESCRIPTION:
DSS Export Rating Curves= 0
DSS Export Rating Curve Sorted= 0
DSS Export Volume Flow Curves= 0
DXF OffsetX= 0
DXF OffsetY= 0
DXF ScaleX= 0
DXF ScaleY= 0

--- GLENNSRUN.p01 (plan) ---

Plan Title=Floodplain
Program Version=4.00
Geom File=g01
Flow File=f01
K Sum by GR=0
Std Step Tol=0.01
Critical Tol=0.01
Num of Std Step Trials=20
Max Error Tol=0.3
Flow Tol Ratio=0.001
Split Flow NTrial=30
Split Flow Tol=0.02
Split Flow Ratio=0.02
Log Output Level=0
Friction Slope Method=1
Unsteady Friction Slope Method=2
Unsteady Bridges Friction Slope Method=1
Global Log Level=0
CheckData=False
Run HTab=0
Run UNet=0
Run PostProcess=0
UNET Theta=0
UNET Theta Warmup=0
UNET ZTol=0
UNET ZSATol=0
UNET MxIter=0
UNET MaxInSteps=0
UNET DtIC=0
UNET DtMin=0
UNET MaxCRTS=0
UNET WFStab=0
UNET SFStab=0
UNET WFX=0
UNET SFX=0
UNET DSS MLevel=0
UNET DZMax Abort=0
UNET Convert EG Bridges=0
UNET Use Existing IB Tables=0
UNET Froude Limit=0
UNET Froude Power=0
Write IC File=0
Echo Input=False
Echo Output=False
Write Detailed=0

--- GLENNSRUN.f01 (steady flow) ---

Flow Title=NFF Regression Equation
Program Version=4.10
Number of Profiles= 1
Profile Names=P100yr
River Rch & RM=GLENNSRUN,Main            ,4230.1
792.0682
River Rch & RM=GLENNSRUN,Main            ,3903.2
967.1175
River Rch & RM=GLENNSRUN,Main            ,1899.7
990.3592
River Rch & RM=GLENNSRUN,Main            ,1153.8
1009.723
Boundary for River Rch & Prof#=GLENNSRUN,Main            , 1
Up Type= 0
Dn Type= 3
Dn Slope=0.007
DSS Import GetInterval= 0
DSS Import GetPeak= 0
DSS Import FillOption= 0

--- GLENNSRUN.g01 (geometry) ---

Geom Title=USGS 10m DEM
Program Version=4.10

River Reach=GLENNSRUN       ,Main
Reach XY= 30
     1634507.036      594113.945     1634443.918      594116.823
     1634254.208      594031.562     1634233.375      593955.174
     1634261.797      593888.594     1634188.214      593719.742
     1634028.911      593615.508     1633931.935      593512.205
     1633898.602      593441.371     1633839.371      593396.758
     1633775.685      593365.677     1633697.009      593357.695
     1633591.658      593305.955     1633520.824      593319.844
     1633452.125      593411.771     1633330.597      593422.187
     1633268.075       593449.56     1633174.347      593446.493
     1633141.361      593479.479     1633060.725      593508.737
     1632937.129      593631.852     1632854.664      593656.808
     1632699.646      593626.425     1632586.797      593635.121
     1632486.102      593685.121      1632299.44      593686.688
     1632031.241      593645.538     1631821.519       593661.51
     1631628.575      593629.852     1630825.053       593607.16

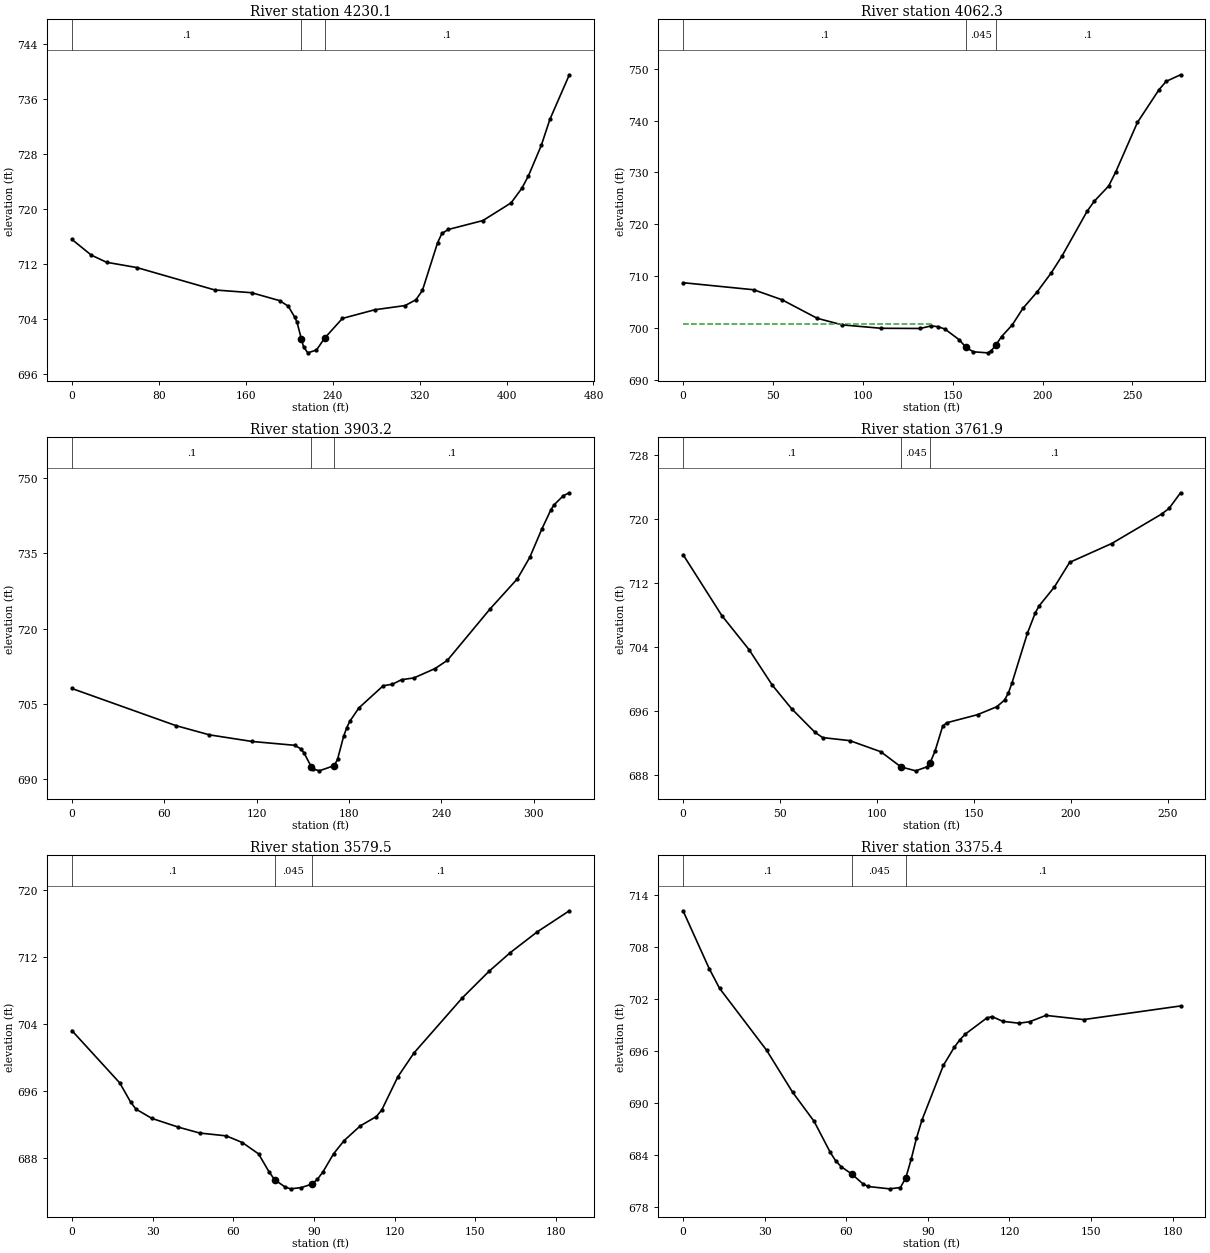
Type RM Length L Ch R = 1 ,4230.1  ,167,167.8,168.2
XS GIS Cut Line= 5
     1634531.096       593916.14     1634450.801      594091.921
     1634395.463      594134.239     1634292.381      594212.364
     1634230.532      594234.065
#Sta/Elev= 30
       0  715.54    17.9  713.25    31.9  712.21    59.8  711.44   131.5  708.18
   165.4  707.78   191.3  706.62   199.2  705.81   205.2  704.18   207.2   703.5
   211.2  701.05   213.2  699.92   217.1  699.03   225.1  699.44   232.7  701.18
     249  704.04   278.8   705.3   306.7  705.91   316.6  706.75   322.6  708.11
   336.5  715.02   340.5   716.4   346.5  716.98   378.3  718.28   404.2  720.85
   414.1  722.97   420.1  724.76     432  729.21   439.9     733   457.8  739.49
#Mann= 3 , 0 , 0
       0      .1       0   211.2    .045       0   232.7      .1       0
Bank Sta=211.2,232.7
XS Rating Curve= 0 ,0
Exp/Cntr=0.3,0.1

Type RM Length L Ch R = 1 ,4062.3  ,143,159.2,174
XS GIS Cut Line= 4
     1634422.589      593979.074       1634356.4      593987.755
     1634239.213       594068.05     1634177.364      594096.261
#Sta/Elev= 30
       0  708.76    39.3   707.4      55  705.48    74.6  701.91    88.5  700.64
   110.2  699.98   131.9  699.94   137.8  700.42   141.7  700.31   145.7  699.83
   153.6  697.78   157.5  696.29   161.5  695.45   169.4  695.25   171.3  695.56
   174.1  696.79   177.2  698.37   183.2  700.65   189.1  703.82     197  706.98
   204.9  710.68   210.8  713.87   224.8  722.51   228.8  724.46   236.8  727.38
   240.8  730.14   252.8  739.62   264.8  745.93   268.8  747.54   276.8  748.81
#Mann= 3 , 0 , 0
       0      .1       0   157.5    .045       0   174.1      .1       0
#XS Ineff= 2 , 0
          137.92  700.82
Permanent Ineff=
       F       F
Bank Sta=157.5,174.1
XS Rating Curve= 0 ,0
Exp/Cntr=0.3,0.1

Type RM Length L Ch R = 1 ,3903.2  ,160.5,141.3,121.7
XS GIS Cut Line= 4
     1634418.394       593942.76     1634348.949      593918.455
     1634220.766      593906.374     1634107.919      593949.777
#Sta/Elev= 30
       0  708.07    67.6  700.68    89.4  698.84   117.2  697.52   144.9  696.76
   148.8  696.04   150.8  695.27   155.5  692.52   156.8  692.07   160.7  691.68
   170.5  692.72   172.6  693.96   176.6  698.59   178.6  700.26   180.5   701.5
   186.5  704.21   202.3  708.62   208.3  708.92   214.2  709.82   222.2  710.17
     236  712.04     244  713.68   271.7   723.9   289.5  729.92   297.5  734.17
   305.4  739.84   311.3  743.68   313.3  744.62   319.3  746.44   323.2  747.02
#Mann= 3 , 0 , 0
       0      .1       0   155.5    .045       0   170.5      .1       0
Bank Sta=155.5,170.5
XS Rating Curve= 0 ,0
Exp/Cntr=0.3,0.1

Type RM Length L Ch R = 1 ,3761.9  ,181.9,182.4,181.8
XS GIS Cut Line= 4
     1634297.806      593691.531     1634261.999      593737.104
      1634191.47      593802.208     1634111.174      593866.227
#Sta/Elev= 30
       0  715.56      20  707.93      34  703.68      46  699.23      56  696.27
      68  693.33      72  692.66      86  692.28     102  690.89   112.4  688.99
     120   688.5     126  689.02   127.4  689.48     130     691   133.9  694.08
   135.9  694.51   151.9  695.53   161.8  696.52   165.8  697.35   167.8  698.24
   169.7  699.53   177.6  705.71   181.6  708.23   183.6  709.13   191.5   711.5
   199.4  714.59   221.1  716.95   246.8  720.63   250.7  721.35   256.6   723.3
#Mann= 3 , 0 , 0
       0      .1       0   112.4    .045       0   127.4      .1       0
Bank Sta=112.4,127.4
XS Rating Curve= 0 ,0
Exp/Cntr=0.3,0.1

Type RM Length L Ch R = 1 ,3579.5  ,194.8,204.1,212.8
XS GIS Cut Line= 3
     1634151.322      593602.555     1634106.834      593644.873
     1634018.944      593731.678
#Sta/Elev= 30
       0  703.19    17.8  696.94    21.8  694.68    23.8  693.82    29.7  692.71
    39.6  691.66    47.5  690.96    57.4  690.62    63.4  689.82    69.4  688.47
    73.3  686.32    75.4  685.38    79.3  684.51    81.3   684.3    85.3  684.45
    89.3  684.88    91.3  685.45    93.3  686.31    97.3  688.49   101.2  690.06
   107.2  691.81   113.2  692.93   115.2  693.72   121.2  697.69   127.2  700.53
   145.1  707.08     155  710.24     163   712.5     173  714.97   184.9  717.48
#Mann= 3 , 0 , 0
       0      .1       0    75.4    .045       0    89.3      .1       0
Bank Sta=75.4,89.3
XS Rating Curve= 0 ,0
Exp/Cntr=0.3,0.1

Type RM Length L Ch R = 1 ,3375.4  ,159.3,147.6,135.1
XS GIS Cut Line= 4
     1634008.093      593502.729      1633969.03      593512.494
     1633913.692      593534.196     1633860.523      593598.215
#Sta/Elev= 30
       0  712.14     9.6  705.48    13.4  703.21    30.7  696.07    40.3  691.21
    48.2  687.86    54.1   684.3    56.1  683.32    58.1  682.65    62.1  681.78
      66   680.7      68  680.36    75.9  680.09    79.9  680.24    81.9  681.37
    83.9  683.54    85.8  685.91    87.8  687.99    95.7  694.32    99.7   696.4
   101.7  697.24   103.7  697.91   111.6  699.77   113.6  699.95   117.5   699.4
   123.5  699.18   127.4  699.35   133.4  700.08   147.3   699.6   182.9  701.17
#Mann= 3 , 0 , 0
       0      .1       0    62.1    .045       0    81.9      .1       0
Bank Sta=62.1,81.9
XS Rating Curve= 0 ,0
Exp/Cntr=0.3,0.1

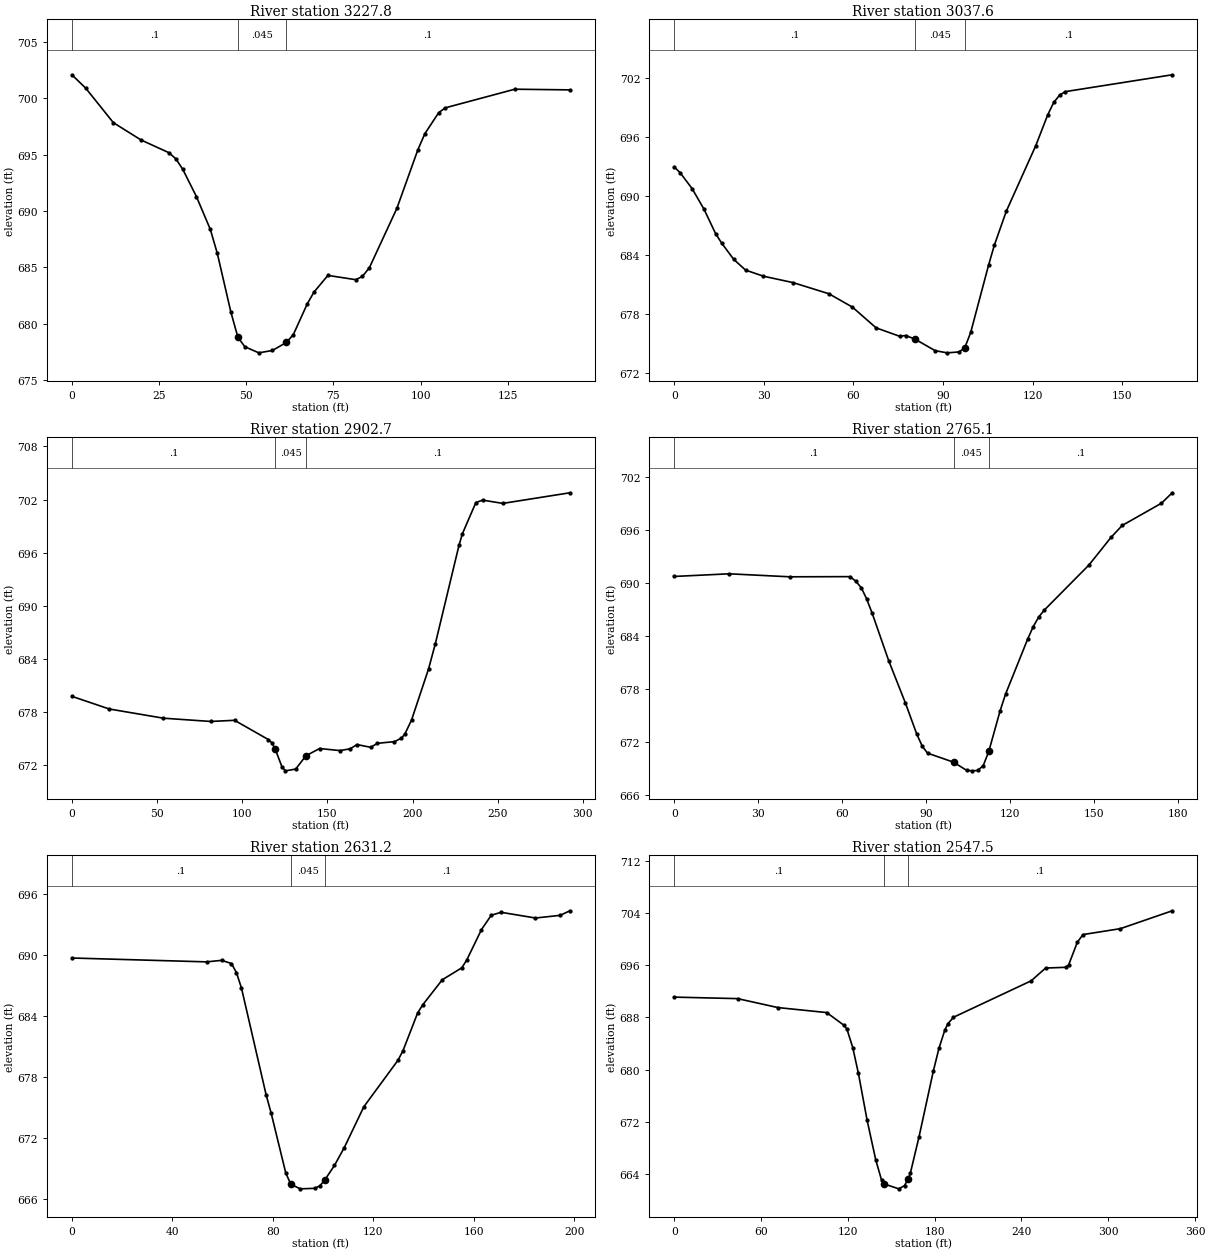
Type RM Length L Ch R = 1 ,3227.8  ,191,190.2,188.3
XS GIS Cut Line= 2
     1633888.735      593367.095     1633799.759      593478.857
#Sta/Elev= 30
       0  702.09       4  700.89    11.9  697.84    19.8  696.31    27.8  695.18
    29.8  694.64    31.8   693.7    35.7  691.29    39.7  688.37    41.7  686.24
    45.6  681.02    47.6   678.8    49.6  677.96    53.6  677.42    57.5  677.63
    61.5  678.34    63.5  679.04    67.5  681.77    69.4   682.8    73.4  684.29
    81.4  683.91    83.3   684.2    85.3  684.97    93.2  690.25    99.2  695.43
   101.2  696.86   105.2  698.74   107.1  699.16     127  700.81   142.8  700.75
#Mann= 3 , 0 , 0
       0      .1       0    47.6    .045       0    61.5      .1       0
Bank Sta=47.6,61.5
XS Rating Curve= 0 ,0
Exp/Cntr=0.3,0.1

Type RM Length L Ch R = 1 ,3037.6  ,157.1,134.9,112.3
XS GIS Cut Line= 4
      1633733.57      593279.204     1633703.188      593316.097
     1633667.381       593366.01     1633665.211      593423.518
#Sta/Elev= 30
       0  692.96       2  692.36       6  690.75      10  688.65    13.9  686.16
    15.9  685.22    19.9  683.58    23.9  682.48    29.9  681.86    39.8  681.21
    51.8  680.08    59.7  678.72    67.6  676.62    75.5  675.76    77.5  675.84
    80.6  675.48    87.4   674.3    91.4  674.08    95.4  674.17    97.3  674.58
    99.3  676.15   105.3     683   107.2  684.99   111.2  688.44   121.1  695.12
   125.1  698.24   127.1   699.5   129.1  700.25     131   700.6   166.8  702.31
#Mann= 3 , 0 , 0
       0      .1       0    80.6    .045       0    97.3      .1       0
Bank Sta=80.6,97.3
XS Rating Curve= 0 ,0
Exp/Cntr=0.3,0.1

Type RM Length L Ch R = 1 ,2902.7  ,138.7,137.7,134.4
XS GIS Cut Line= 4
     1633518.726      593180.463     1633540.428      593267.268
     1633591.426      593399.647     1633608.787      593458.241
#Sta/Elev= 30
       0  679.76    21.9  678.33    53.7  677.29    81.5  676.92    95.5  677.05
   115.4  674.87   117.4  674.52   119.4  673.79   123.4  671.76   125.4  671.34
   131.4  671.54   137.4  673.04   145.4  673.86   157.4  673.63   163.4  673.83
   167.4  674.31   175.4     674   179.4  674.45   189.4  674.64   193.4  675.03
   195.4  675.46   199.4  677.07   209.4  682.85   213.4  685.71   227.3  696.84
   229.3  698.14   237.2  701.66   241.2  701.93     253  701.56   292.4  702.76
#Mann= 3 , 0 , 0
       0      .1       0   119.4    .045       0   137.4      .1       0
Bank Sta=119.4,137.4
XS Rating Curve= 0 ,0
Exp/Cntr=0.3,0.1

Type RM Length L Ch R = 1 ,2765.1  ,128.7,133.8,139.3
XS GIS Cut Line= 3
       1633418.9      593307.416     1633453.622      593373.605
      1633498.11      593466.921
#Sta/Elev= 30
       0   690.7    19.7     691    41.3  690.66    62.9  690.68    64.9  690.17
    66.9  689.42    68.8  688.17    70.8  686.53    76.7  681.17    82.7  676.36
    86.7  672.89    88.7  671.49    90.6   670.7    99.9  669.68   104.6  668.75
   106.6   668.7   108.5  668.74   110.5  669.28   112.5   670.9   116.5  675.45
   118.5  677.39   126.4  683.61   128.4  685.03   130.4  686.13   132.4  686.91
   148.3  691.99   156.2  695.12   160.2  696.47   174.2  698.98   178.1  700.17
#Mann= 3 , 0 , 0
       0      .1       0    99.9    .045       0   112.5      .1       0
Bank Sta=99.9,112.5
XS Rating Curve= 0 ,0
Exp/Cntr=0.3,0.1

Type RM Length L Ch R = 1 ,2631.2  ,78,83.7,89.3
XS GIS Cut Line= 4
     1633316.904      593329.117      1633333.18      593400.732
     1633342.945      593446.305     1633345.115       593524.43
#Sta/Elev= 30
       0   689.7    53.6  689.32    59.6  689.47    63.5  689.16    65.5  688.26
    67.5  686.74    77.3  676.26    79.3  674.46    85.1   668.6    87.1  667.47
    90.9  667.02    96.7  667.07    98.7  667.32   100.6  667.87   104.5  669.32
   108.4  671.07   116.2  675.09   129.8  679.66   131.8  680.61   137.6   684.3
   139.6  685.09   147.4  687.56   155.2  688.74   157.2  689.53     163  692.49
   166.9   693.9   170.8  694.19   184.5  693.63   194.3  693.89   198.2  694.34
#Mann= 3 , 0 , 0
       0      .1       0    87.1    .045       0   100.6      .1       0
Bank Sta=87.1,100.6
XS Rating Curve= 0 ,0
Exp/Cntr=0.3,0.1

Type RM Length L Ch R = 1 ,2547.5  ,108.2,111.9,122.6
XS GIS Cut Line= 2
     1633265.905       593295.48     1633252.884      593639.447
#Sta/Elev= 30
       0  691.12    43.8  690.89    71.6  689.52   105.4  688.75   117.4  686.79
   119.4   686.2   123.4  683.38   127.3  679.43   133.3  672.26   139.3  666.15
   143.3  663.06   145.2  662.46   155.2  661.72   159.2  662.22   161.7  663.27
   163.2  664.12   169.1   669.6   179.1  679.79     183  683.29     187  686.04
     189     687     193  688.03   246.7  693.62   256.7  695.58   270.6  695.69
   272.6  696.06   278.6  699.53   282.5  700.71   308.4  701.62   344.2  704.36
#Mann= 3 , 0 , 0
       0      .1       0   145.2    .045       0   161.7      .1       0
Bank Sta=145.2,161.7
XS Rating Curve= 0 ,0
Exp/Cntr=0.3,0.1

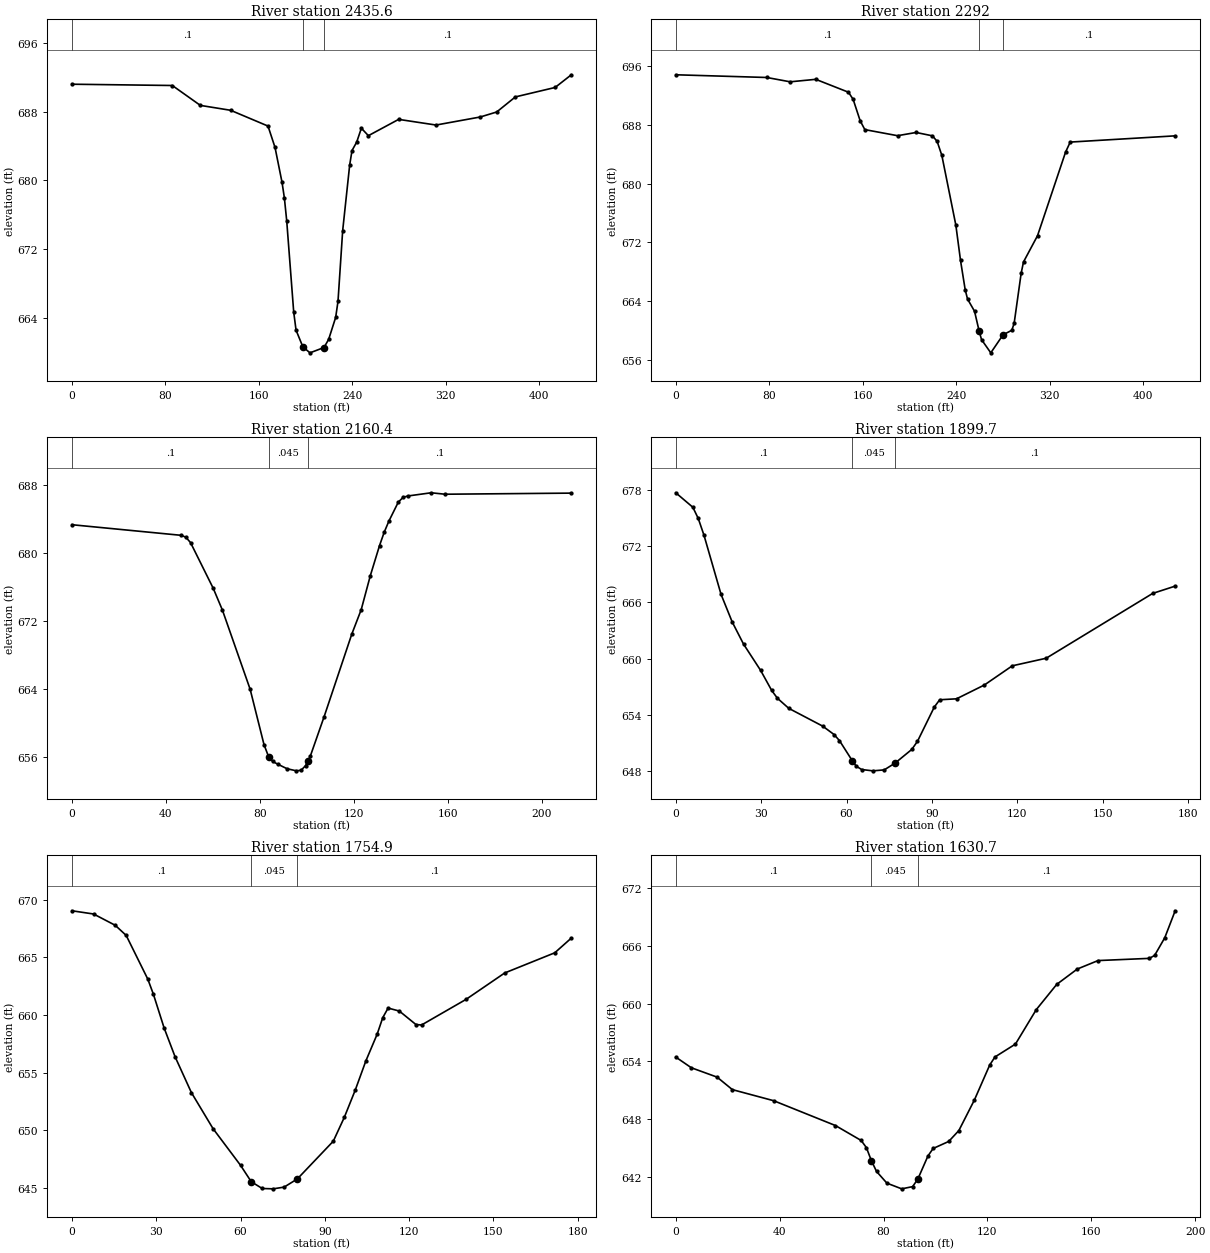
Type RM Length L Ch R = 1 ,2435.6  ,141.6,143.7,137
XS GIS Cut Line= 2
     1633170.419      593255.333     1633141.122      593681.765
#Sta/Elev= 30
       0   691.2    85.9  691.05   109.9  688.73   135.8  688.16   167.8  686.32
   173.8  683.83   179.8  679.76   181.8  677.95   183.8  675.28   189.8  664.62
   191.8  662.52   197.6  660.59   203.7  659.88   215.7   660.5   219.7  661.45
   225.7  664.01   227.7  665.89   231.7  674.13   237.7  681.79   239.7  683.47
   243.7  684.45   247.7  686.07   253.7   685.2   279.6   687.1   311.6  686.44
   349.5  687.38   363.5  687.96   379.5  689.72   413.5  690.82   427.4   692.3
#Mann= 3 , 0 , 0
       0      .1       0   197.6    .045       0   215.7      .1       0
Bank Sta=197.6,215.7
XS Rating Curve= 0 ,0
Exp/Cntr=0.3,0.1

Type RM Length L Ch R = 1 ,2292    ,146.1,131.6,116
XS GIS Cut Line= 2
     1633054.317      593258.588      1633025.02       593685.02
#Sta/Elev= 30
       0  694.85    77.9  694.48    97.9  693.89   119.8  694.23   147.8  692.47
   151.8   691.5   157.8  688.58   161.8  687.37   189.8  686.54   205.7  686.98
   219.7  686.52   223.7  685.76   227.7  683.86   239.7  674.34   243.7  669.52
   247.7  665.52   249.7  664.26   255.7  662.59   259.7  659.84   261.7  658.72
   269.6  656.92   280.1  659.38   287.6     660   289.6  660.95   295.6  667.78
   297.6  669.32   309.6   672.9   333.6   684.3   337.6  685.67   427.4  686.52
#Mann= 3 , 0 , 0
       0      .1       0   259.7    .045       0   280.1      .1       0
Bank Sta=259.7,280.1
XS Rating Curve= 0 ,0
Exp/Cntr=0.3,0.1

Type RM Length L Ch R = 1 ,2160.4  ,258,260.7,262.7
XS GIS Cut Line= 4
     1632907.832      593540.706     1632936.044      593598.215
     1632964.256      593661.149     1632972.937      593740.359
#Sta/Elev= 30
       0  683.37    46.6  682.12    48.5   681.9    50.5  681.27    60.2  675.87
    64.1  673.31    75.9     664    81.8  657.49    83.8  656.03    85.5   655.5
    87.7  655.18    91.6  654.65    95.6   654.4    97.6  654.47    99.5  655.01
   100.5  655.56   101.5  656.11   107.4  660.77   119.2   670.5   123.2  673.37
   127.1  677.39     131  680.91     133  682.49     135   683.8     139  686.03
     141  686.58     143  686.75     153  687.13   158.9  686.96   212.7  687.09
#Mann= 3 , 0 , 0
       0      .1       0    83.8    .045       0   100.5      .1       0
Bank Sta=83.8,100.5
XS Rating Curve= 0 ,0
Exp/Cntr=0.3,0.1

Type RM Length L Ch R = 1 ,1899.7  ,147.7,144.8,139
XS GIS Cut Line= 4
     1632671.866      593562.552     1632694.435      593611.163
     1632708.324      593658.038     1632706.588      593730.955
#Sta/Elev= 30
       0  677.73       6  676.18     7.9  674.98     9.9   673.2    15.9  666.87
    19.8  663.93    23.8  661.55    29.8  658.74    33.7  656.59    35.7  655.76
    39.7  654.68    51.6  652.78    55.6  651.88    57.5  651.23      62  649.08
    63.4  648.49    65.3  648.14    69.2     648    73.2   648.1      77  648.82
    82.9  650.29    84.9  651.16    90.8  654.82    92.7   655.6    98.6   655.7
   108.4  657.18   118.2  659.23   130.1  660.04   167.5  666.97   175.4  667.75
#Mann= 3 , 0 , 0
       0      .1       0      62    .045       0      77      .1       0
Bank Sta=62,77
XS Rating Curve= 0 ,0
Exp/Cntr=0.3,0.1

Type RM Length L Ch R = 1 ,1754.9  ,111.2,124.2,136.6
XS GIS Cut Line= 4
     1632521.548      593583.024     1632546.504      593622.086
     1632574.716      593673.084     1632597.503      593742.529
#Sta/Elev= 30
       0  669.05     7.7  668.77    15.4  667.79    19.3  666.91      27  663.11
      29  661.79    32.8  658.87    36.7  656.37    42.5  653.26    50.2  650.13
      60  646.94    63.8  645.52    67.7  644.93    71.6   644.9    75.5  645.05
    80.2  645.76      93  649.04    96.9   651.1   100.8  653.47   104.6  656.02
   108.6  658.33   110.6  659.77   112.5   660.6   116.5  660.34   122.4  659.17
   124.4  659.13   140.2  661.35     154  663.65   171.8   665.4   177.7  666.68
#Mann= 3 , 0 , 0
       0      .1       0    63.8    .045       0    80.2      .1       0
Bank Sta=63.8,80.2
XS Rating Curve= 0 ,0
Exp/Cntr=0.3,0.1

Type RM Length L Ch R = 1 ,1630.7  ,153.6,152.7,151.6
XS GIS Cut Line= 2
     1632451.018      593600.385     1632441.253      593792.442
#Sta/Elev= 30
       0  654.45       6  653.34    15.9  652.37    21.8  651.07    37.7  649.92
    61.5  647.34    71.4  645.79    73.4  645.05    75.3  643.71    77.3  642.58
    81.3  641.36      87  640.77    91.2     641    93.2  641.78    97.1  644.18
    99.1  644.96   105.1  645.69     109  646.82     115     650   120.9  653.63
   122.9  654.46   130.8   655.8   138.8  659.37   146.7     662   154.6  663.59
   162.6  664.47   182.4   664.7   184.4  665.01   188.3  666.84   192.3  669.64
#Mann= 3 , 0 , 0
       0      .1       0    75.3    .045       0    93.2      .1       0
Bank Sta=75.3,93.2
XS Rating Curve= 0 ,0
Exp/Cntr=0.3,0.1

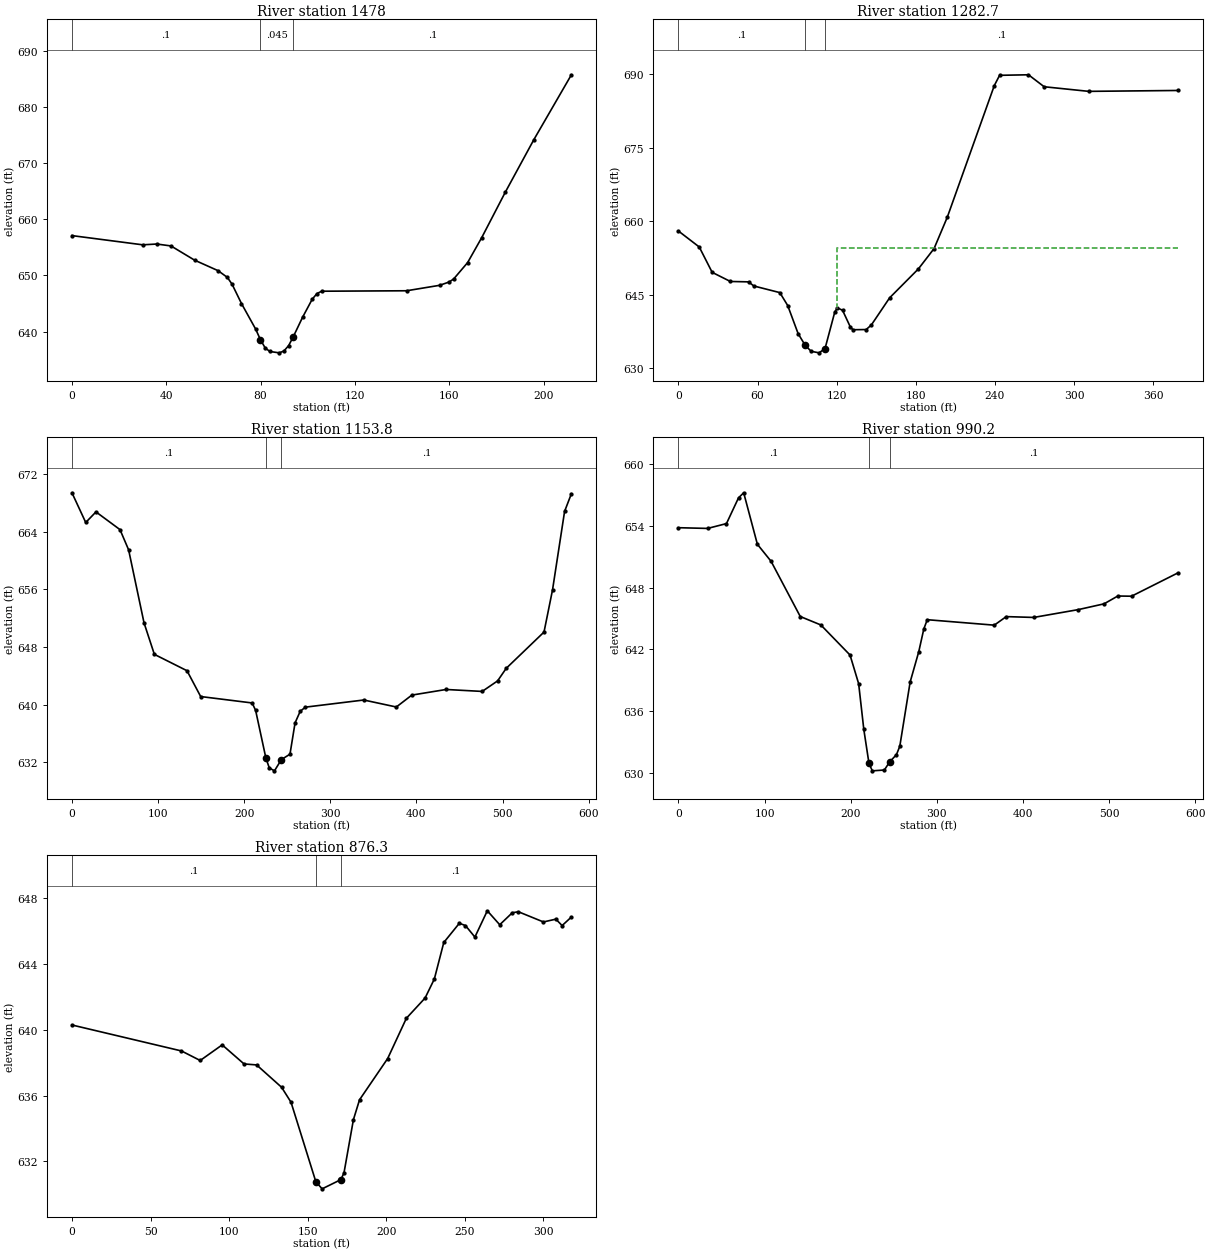
Type RM Length L Ch R = 1 ,1478    ,195.4,195.3,195.3
XS GIS Cut Line= 2
      1632295.13      593595.538     1632293.394      593807.344
#Sta/Elev= 30
       0  657.08      30  655.44      36  655.58      42  655.24      52  652.71
      62  650.83    65.9  649.64    67.9  648.43    71.9  644.98    77.9  640.44
    79.9  638.58    81.9  637.11    83.9  636.45    87.9  636.21    89.9  636.54
    91.9   637.5    93.9  639.11    97.8  642.54   101.9  645.76   103.9  646.76
   105.9  647.18   141.9  647.26   155.9  648.23   159.9  648.81   161.9  649.37
   167.8  652.28   173.8  656.74   183.8  664.83   195.8   674.1   211.8  685.71
#Mann= 3 , 0 , 0
       0      .1       0    79.9    .045       0    93.9      .1       0
Bank Sta=79.9,93.9
XS Rating Curve= 0 ,0
Exp/Cntr=0.3,0.1

Type RM Length L Ch R = 1 ,1282.7  ,130.5,128.9,126.8
XS GIS Cut Line= 4
     1632138.518      593565.663     1632101.626      593628.597
     1632100.541      593743.614      1632160.22      593924.821
#Sta/Elev= 30
       0  658.03    15.8  654.77    25.6   649.6    39.4  647.74    53.2  647.66
    57.2  646.82    76.9  645.47    82.9  642.83    90.8   637.1    96.2   634.7
   100.7   633.5   106.7  633.19   111.2  634.06   118.6  641.52   120.6  642.37
   124.5  641.86   130.5   638.4   132.4   637.9   142.4  637.94   146.3  638.86
   160.2  644.41     182   650.3   193.9  654.45   203.9  660.82   239.6  687.69
   243.6  689.77   265.5  689.88   277.4  687.44   311.2   686.5   378.8  686.68
#Mann= 3 , 0 , 0
       0      .1       0    96.2    .045       0   111.2      .1       0
#XS Ineff= 2 , 0
                          120.11          654.64
Permanent Ineff=
       F       F
Bank Sta=96.2,111.2
XS Rating Curve= 0 ,0
Exp/Cntr=0.3,0.1

Type RM Length L Ch R = 1 ,1153.8  ,163.6,163.6,163.6
XS GIS Cut Line= 2
     1631956.226      593414.838     1632000.714       593993.18
#Sta/Elev= 30
       0  669.37      16  665.25    27.9  666.72    55.8  664.26    65.8  661.46
    83.7  651.34    95.7  646.97   133.6   644.7   149.5  641.12   209.3  640.23
   213.3   639.2   225.2   632.6   229.2  631.22   235.2  630.82   243.2  632.38
   253.2  633.13   259.1  637.47   265.1  639.08   271.1  639.65   338.9  640.64
   376.7  639.67   394.7  641.32   434.5   642.1   476.4  641.83   494.3  643.29
   504.3  645.03   548.2  650.06   558.1  655.91   572.1  666.79     580  669.24
#Mann= 3 , 0 , 0
       0      .1       0   225.2    .045       0   243.2      .1       0
Bank Sta=225.2,243.2
XS Rating Curve= 0 ,0
Exp/Cntr=0.3,0.1

Type RM Length L Ch R = 1 ,990.2   ,112.3,113.8,115.5
XS GIS Cut Line= 2
     1631793.466      593430.029     1631837.954      594008.371
#Sta/Elev= 30
       0  653.82    33.9  653.75    55.8  654.22    69.8  656.72    75.8  657.21
    91.7  652.21   107.6  650.56   141.5   645.2   165.4  644.38   199.3  641.46
   209.3  638.68   215.3  634.24   221.3  630.94   225.2  630.22   239.2   630.3
   245.2  631.08   253.2  631.79   257.1  632.61   269.1  638.84   279.1  641.78
     285     644     289  644.89   366.8  644.36   380.7  645.19   412.6  645.11
   464.4  645.87   494.3  646.43   510.3  647.19   526.2  647.17     580  649.43
#Mann= 3 , 0 , 0
       0      .1       0   221.3    .045       0   245.2      .1       0
Bank Sta=221.3,245.2
XS Rating Curve= 0 ,0
Exp/Cntr=0.3,0.1

Type RM Length L Ch R = 1 ,876.3   ,875.3,876.3,876.9
XS GIS Cut Line= 4
     1631725.685      593493.108     1631697.908       593621.58
     1631697.908      593691.024     1631734.366      593802.135
#Sta/Elev= 30
       0   640.3    69.7  638.72    81.6  638.14    95.6  639.09   109.5  637.93
   117.5  637.87   133.4  636.51   139.4   635.6   155.2  630.76   159.2  630.33
   171.1  630.89   173.1   631.3   179.1  634.54     183  635.75   200.9  638.26
   212.8  640.71   224.7  641.94   230.6   643.1   236.6  645.32   246.5  646.49
   250.4  646.35   256.4  645.65   264.3  647.25   272.2   646.4   280.2  647.13
   284.1  647.19     300  646.57   307.9  646.74   311.9  646.35   317.8  646.87
#Mann= 3 , 0 , 0
       0      .1       0   155.2    .045       0   171.1      .1       0
Bank Sta=155.2,171.1
XS Rating Curve= 0 ,0
Exp/Cntr=0.3,0.1

Chan Stop Cuts=-1
Use User Specified Reach Order=0
Composite Channel Slope=5